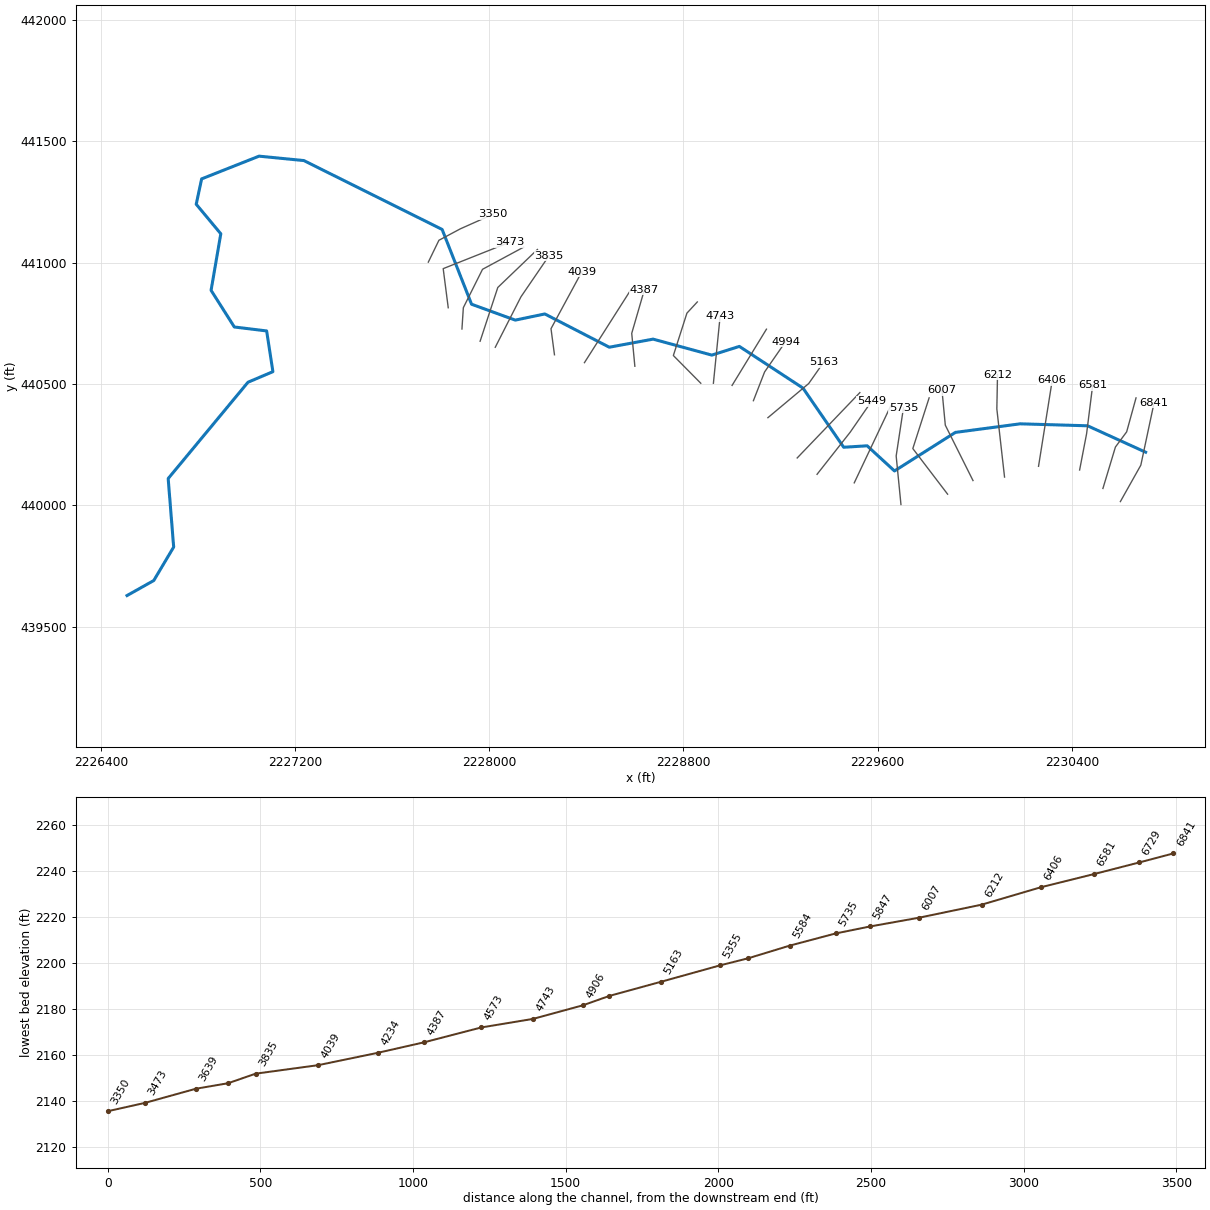
--- STLHSRN.prj (project) ---

Proj Title=STLHSRN
Current Plan=p01
Default Exp/Contr=0,0
English Units
Geom File=g01
Flow File=f01
Plan File=p01
Background Map Layer=Inundation Boundary (01pct Value_0)
BEGIN DESCRIPTION:
----------MODEL BY WOOD PLC 2021----------
Stream Name: Stillhouse Run
Flood Zone: Enhanced Approximate
Pocahontas County, WV
HEC-RAS Version: RAS 6.1
Vertical Datum: NAVD88
Projection: NAD 1983 StatePlane West Virginia S FIPS 4702 (US Feet)
Terrain: 1-meter LIDAR (FEMA Region III 3DEP collected 2016-2018)
Land Use: 2019 NLCD
Hydrologic Method:
WV SIR2010-5033 regression equations
Model Notes:
Normal depth tie in to Greenbrier River
END DESCRIPTION:
DSS Export Rating Curves= 0
DSS Export Rating Curve Sorted= 0
DSS Export Volume Flow Curves= 0
DXF OffsetX= 0
DXF OffsetY= 0
DXF ScaleX= 0
DXF ScaleY= 0

--- STLHSRN.p01 (plan) ---

Plan Title=Floodplain
Program Version=6.10
Short Identifier=Floodplain
Geom File=g01
Flow File=f01
Subcritical Flow
K Sum by GR= 0
Std Step Tol= 0.01
Critical Tol= 0.01
Num of Std Step Trials= 20
Max Error Tol= 0.3
Flow Tol Ratio= 0.001
Split Flow NTrial= 30
Split Flow Tol= 0.02
Split Flow Ratio= 0.02
Log Output Level= 0
Friction Slope Method= 1
Unsteady Friction Slope Method= 2
Unsteady Bridges Friction Slope Method= 1
Parabolic Critical Depth
Global Vel Dist= 0 , 0 , 0
Global Log Level= 0
CheckData=True
Encroach Param=-1 ,0,0, 0
Mapping Interval=1HOUR
Computation Time Step Use Courant=        0
Computation Time Step Use Time Series=    0
Computation Time Step Count To Double=0
Computation Time Step Max Doubling=0
Computation Time Step Max Halving=0
Computation Time Step Residence Courant=0
Run HTab= 0
Run UNet= 0
Run Sediment= 0
Run PostProcess= 0
Run WQNet= 0
Run RASMapper=-1
UNET Theta= 0
UNET Theta Warmup= 0
UNET ZTol= 0
UNET ZSATol= 0
UNET MxIter= 0
UNET Max Iter WO Improvement= 0
UNET MaxInSteps= 0
UNET DtIC= 0
UNET DtMin= 0
UNET MaxCRTS= 0
UNET WFStab= 0
UNET SFStab= 0
UNET WFX= 1
UNET SFX= 1
UNET Gravity=32.174
UNET 1D Methodology=Finite Difference
UNET DSS MLevel= 1
UNET Pardiso=0
UNET DZMax Abort= 0
UNET Use Existing IB Tables= 0
UNET Froude Reduction=False
UNET Froude Limit= 0
UNET Froude Power= 0
UNET D1 Cores= 0
UNET WindReference=Eulerian
UNET WindDragFormulation=Hsu (1988)
UNET D2 Coriolis=0
UNET D2 Cores= 0
UNET D2 Theta= 1
UNET D2 Theta Warmup= 1
UNET D2 Z Tol= 0.01
UNET D2 Volume Tol= 0.01
UNET D2 Max Iterations= 20
UNET D2 Equation= 0
UNET D2 RampUpFraction=0.1
UNET D2 TimeSlices= 1
UNET D2 Turbulence Formulation=Non-Conservative (original)
UNET D2 Eddy Viscosity=0.3
UNET D2 Transverse Eddy Viscosity=0.1
UNET D2 Smagorinsky Mixing=0
UNET D2 BCVolumeCheck=0
UNET D2 Cores=0
UNET D2 SolverType=PARDISO (Direct)
UNET D2 Minimum Iterations= 2147483647
UNET D2 Maximum Iterations= 2147483647
UNET D2 Restart Number= 10
UNET D2 Relaxation Coeff=1.3
UNET D2 SOR Precondition Iterations= 10
UNET D2 ILUT Maximum Fill= 8
UNET D2 ILUT Tolerance=1E-08
UNET D1D2 MaxIter= 0
UNET D1D2 ZTol=0.01
UNET D1D2 QTol=0.1
UNET D1D2 MinQTol=1
Write IC File= 0
Write IC File at Fixed DateTime=0
Write IC File at Sim End=0
Echo Input=False
Echo Parameters=False
Echo Output=False
Write Detailed= 0
HDF Write Warmup=0
HDF Write Time Slices=0
HDF Flush=0
HDF Compression= 1
HDF Chunk Size= 1
HDF Spatial Parts= 1
HDF Use Max Rows=0
HDF Fixed Rows= 1
Calibration Method= 0
Calibration Iterations= 20
Calibration Max Change=0.05
Calibration Tolerance=0.2
Calibration Maximum=1.5
Calibration Minimum=0.5
Calibration Optimization Method= 1
WQ AD Non Conservative
WQ ULTIMATE=-1
WQ Max Comp Step=1HOUR
WQ Output Interval=15MIN
WQ Output Selected Increments= 0
WQ Output face flow=0
WQ Output face velocity=0
WQ Output face area=0
WQ Output face dispersion=0
WQ Output cell volume=0
WQ Output cell surface area=0
WQ Output cell continuity=0
WQ Output cumulative cell continuity=0
WQ Output face conc=0
WQ Output face dconc_dx=0
WQ Output face courant=0
WQ Output face peclet=0
WQ Output face adv mass=0
WQ Output face disp mass=0
WQ Output cell mass=0
WQ Output cell source sink temp=0
WQ Output nsm pathways=0
WQ Output nsm derived pathways=0
WQ Create Restart=0
WQ Fixed Restart=0
WQ System Summary=0
WQ Write To DSS=0
Sorting and Armoring Iterations= 10
XS Update Threshold= 0.02
Bed Roughness Predictor= 0
Hydraulics Update Threshold= 0.02
Energy Slope Method= 1
Volume Change Method= 1
Sediment Retention Method= 0
Sediment TS Multiplier= 1
Warm Up Method= 0
XS Weighting Method= 0
Number of US Weighted Cross Sections= 1
Number of DS Weighted Cross Sections= 1
Upstream XS Weight=0
Main XS Weight=1
Downstream XS Weight=0
Number of DS XS's Weighted with US Boundary= 1
Upstream Boundary Weight= 1
Weight of XSs Associated with US Boundary= 0
Number of US XS's Weighted with DS Boundary= 1
Downstream Boundary Weight= 0.5
Weight of XSs Associated with DS Boundary= 0.5
Percentile Method= 0
Sediment Output Level= 3
Mass or Volume Output= 0
Output Increment Type= 1
Profile and TS Output Increment= 1
Transport Output Increment 1
XS Output Flag= 0
XS Output Increment= 10
Read HDF5 Sediment Hotstart= 0
Sediment Hotstart Type= 0
Write Gradation File= 0
Read Gradation Hotstart= 0
Write HDF5 File= 1
Write Binary Output= 1
Write DSS Sediment File= 0
DSS Sediment Output Type= 1
SV Curve= 0
Specific Gage Flag= 0
Subcell Erosion Methods= 0
Subcell Deposition Methods= 0
Advection Scheme= 1
Matrix Solver= 0
Implicit Weighting Factor= 1
Maximum Outer Loop Convergence Iterations= 5
Convergence Maximum Absolute= 0.001
Convergence RMSE= 0.0001
Grain Fractions Max Abs Error= 0.001
Max Subgrid Regions= 1
Max Subgrid Length Scale= 3.402823E+38
Initial Layer Thickness= 3.402823E+38
Min Layer Thickness= 3.402823E+38
Max Layer Thickness= 3.402823E+38
Number of Layers= 5

--- STLHSRN.f01 (steady flow) ---

Flow Title=Flow
Program Version=6.10
Number of Profiles= 6
Profile Names=01pct,10pct,04pct,02pct,0_2pct,01plus
River Rch & RM=STLHSRN,Main,6841
     645     342     454     546     898     953
Boundary for River Rch & Prof#=STLHSRN,Main            , 1
Up Type= 0
Dn Type= 3
Dn Slope=0.0294
Boundary for River Rch & Prof#=STLHSRN,Main            , 2
Up Type= 0
Dn Type= 3
Dn Slope=0.0294
Boundary for River Rch & Prof#=STLHSRN,Main            , 3
Up Type= 0
Dn Type= 3
Dn Slope=0.0294
Boundary for River Rch & Prof#=STLHSRN,Main            , 4
Up Type= 0
Dn Type= 3
Dn Slope=0.0294
Boundary for River Rch & Prof#=STLHSRN,Main            , 5
Up Type= 0
Dn Type= 3
Dn Slope=0.0294
Boundary for River Rch & Prof#=STLHSRN,Main            , 6
Up Type= 0
Dn Type= 3
Dn Slope=0.0294
DSS Import GetInterval= 0
DSS Import GetPeak= 0
DSS Import FillOption= 0

--- STLHSRN.g01 (geometry) ---

Geom Title=Geometry
Program Version=6.10

River Reach=STLHSRN         ,Main
Reach XY= 30
     2230704.148      440218.6852230465.10978341      440327.449
     2230187.463      440335.549     2229920.371      440300.199
      2229669.52      440141.349     2229556.978      440244.978
     2229460.258      440239.0342229292.50819245440482.806050695
2229030.39794745440654.511025088     2228917.003      440618.694
     2228675.019      440684.466     2228494.554      440651.176
     2228228.934      440788.2172228107.15851127440762.802230529
     2227927.083      440828.261     2227805.954      441136.299
     2227236.257      441420.162     2227051.577      441438.317
      2226815.07      441344.686     2226792.704      441240.199
     2226893.975      441118.472     2226853.949       440885.48
      2226949.76      440734.488     2227082.822      440718.282
     2227108.665      440550.461     2227005.902       440506.78
     2226677.157      440110.037     2226699.838      439827.873
     2226617.777      439689.885     2226507.612      439628.041

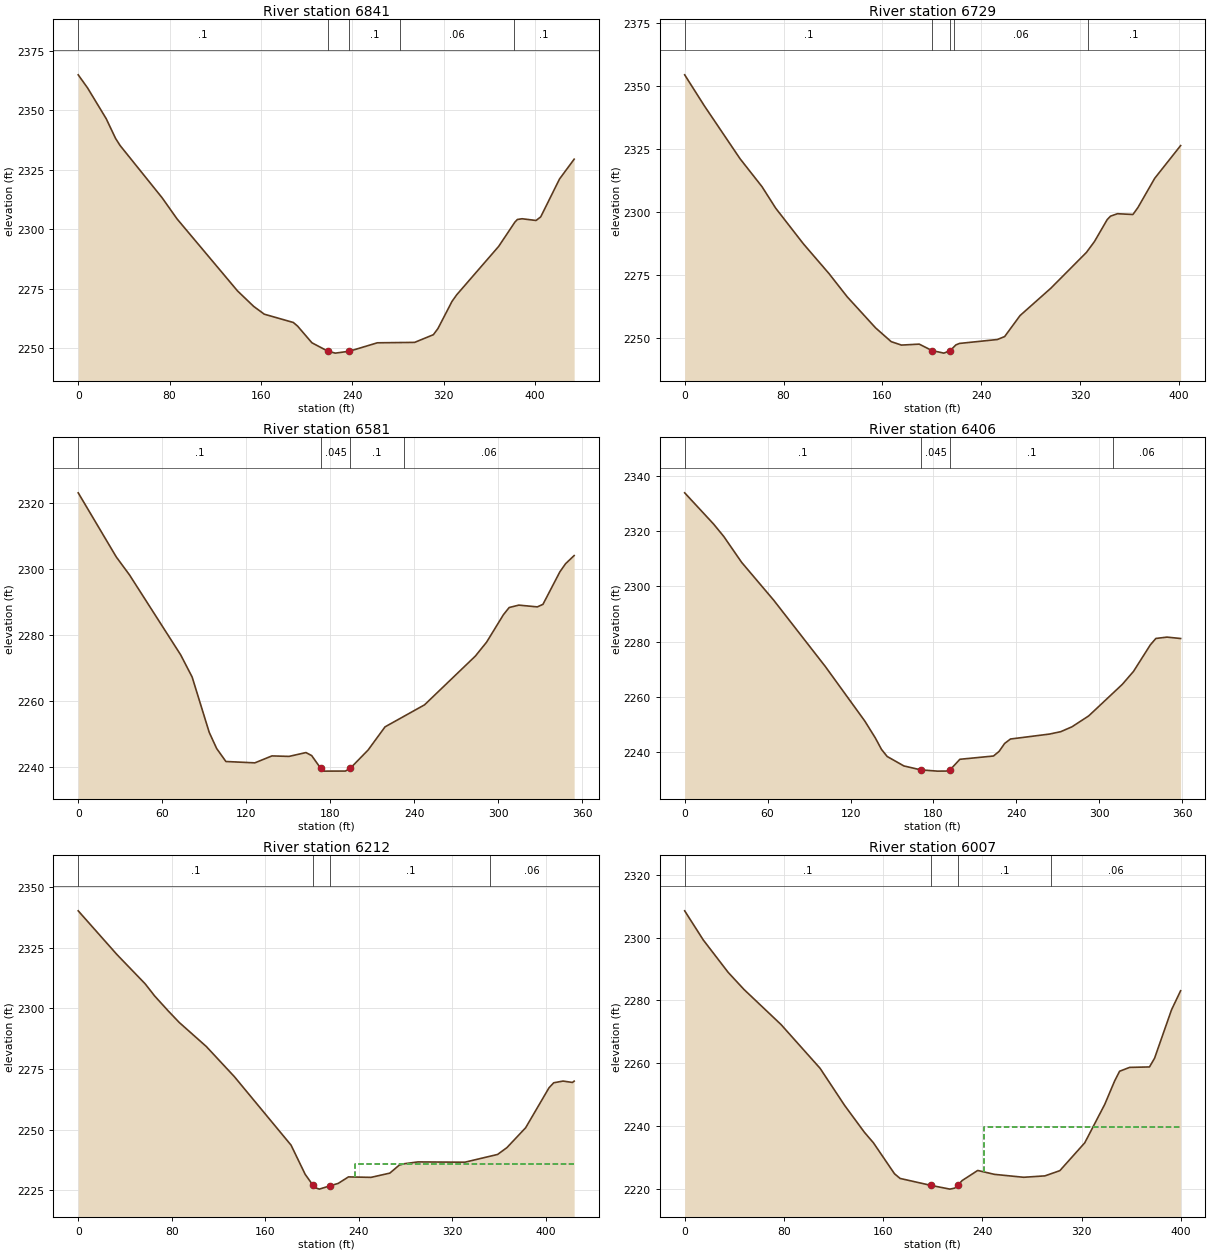
Type RM Length L Ch R = 1 ,6841    ,259.6,112.1,259.6
XS GIS Cut Line= 3
2230600.17851455440015.1941356722230684.41318939440165.170406227
2230738.96680612440421.868975823
#Sta/Elev= 30
       0 2364.85     8.2 2359.34    24.5 2346.42    32.7 2338.14    36.7 2335.12
    73.5 2313.15    86.6 2304.25   139.5 2274.01   153.7 2267.48     163  2264.2
   188.4 2260.72   192.1 2259.22   204.7 2252.18218.72312248.644   225.2 2247.83
   237.5 2248.62     262 2252.17   294.7 2252.35   311.1 2255.58   315.1 2258.17
   327.4 2269.57   331.5 2272.34   368.3 2292.72   382.5 2302.92   384.7 2304.03
   388.8 2304.33     401 2303.61   405.1 2305.11   421.6 2321.06   434.4 2329.38
#Mann= 5 ,-1,0
       0      .1       0218.7231    .045       0   237.5      .1       0
  282.01     .06       0  382.01      .1       0
Bank Sta=218.7231,237.5
XS Rating Curve= 0 ,0
Exp/Cntr=0.3,0.1

Type RM Length L Ch R = 1 ,6729    ,139,147.4,154.6
XS GIS Cut Line= 4
2230528.28942517440069.2214347052230579.75989125440239.931813846
2230626.08331071440302.5542142352230664.68616027440442.382313732
#Sta/Elev= 30
       0 2354.34    15.9 2342.05    44.8 2321.04    62.6 2309.93    73.7 2301.38
      96  2287.3   116.9 2275.38   131.5 2266.24   154.5 2253.89   167.1 2248.44
   175.4 2247.07   189.8 2247.45  200.06 2244.91   209.7 2243.88   214.7 2244.81
   219.5 2247.16   222.4 2247.73     253 2249.28   258.9 2250.45   271.4  2258.8
   296.3 2269.65   325.1 2283.86   331.6 2288.18   341.9 2296.88   344.6 2298.25
   350.2 2299.21   362.7  2298.9   366.8  2301.7   380.3 2313.24   401.3 2326.26
#Mann= 5 ,-1,0
       0      .1       0  200.06    .045       0   214.7      .1       0
   218.3     .06       0  326.19      .1       0
Bank Sta=200.06,214.7
XS Rating Curve= 0 ,0
Exp/Cntr(USF)=0,0
Exp/Cntr=0.3,0.1

Type RM Length L Ch R = 1 ,6581    ,175.2,175.2,175.2
XS GIS Cut Line= 3
2230432.24423338 440145.27754947 2230461.0300696 440294.96389777
2230486.14382126440495.231354877
#Sta/Elev= 30
       0 2322.95    27.2 2303.57    36.6 2298.17    73.2 2273.98    81.4 2267.27
    93.6 2250.55    98.9 2245.68   105.5 2241.75   126.2 2241.34   138.4 2243.44
   150.6 2243.29   162.7 2244.45   166.8 2243.53173.28692239.657   174.8 2238.84
   190.9 2238.86194.33692239.689   207.1 2245.22   219.2 2252.22   247.4 2258.87
   283.7  2273.6   291.7 2277.79   303.8 2286.13   307.9 2288.29   314.8 2289.01
     328 2288.48     332 2289.24   344.1 2299.07   348.2 2301.54   354.3 2303.99
#Mann= 4 ,-1,0
       0      .1       0173.2869    .045       0194.3369      .1       0
  232.43     .06       0
Bank Sta=173.2869,194.3369
XS Rating Curve= 0 ,0
Exp/Cntr(USF)=0,0
Exp/Cntr=0.3,0.1

Type RM Length L Ch R = 1 ,6406    ,193.4,193.4,193.4
XS GIS Cut Line= 2
2230262.99601895440160.5096514092230319.40375544440514.887686427
#Sta/Elev= 30
       0 2333.96    20.9 2322.65    28.3 2318.13    41.2 2308.76    64.5 2294.98
   101.9 2270.89   130.3 2251.23   137.9 2245.12   142.4 2240.93   146.5 2238.37
   158.6 2234.94170.87032233.505   182.9 2233.06     191 2233.09   192.1 2233.57
   199.1 2237.35   223.4 2238.54   227.5 2240.23   231.5  2243.1   235.7  2244.7
     264  2246.5   272.1 2247.37   280.2 2249.13   292.3 2253.08   316.6 2264.51
   324.7 2269.21   336.9 2278.84   340.9 2281.16     349 2281.65   358.8 2281.14
#Mann= 4 ,-1,0
       0      .1       0170.8703    .045       0   192.1      .1       0
     310     .06       0
Bank Sta=170.8703,192.1
XS Rating Curve= 0 ,0
Exp/Cntr(USF)=0,0
Exp/Cntr=0.3,0.1

Type RM Length L Ch R = 1 ,6212    ,200.7,205.4,211.5
XS GIS Cut Line= 3
2230122.92413994440116.2255209812230091.21366277 440396.95651005
2230094.01164605440538.720996225
#Sta/Elev= 30
       0 2340.25    33.2 2322.19    57.3 2310.14    65.4 2305.14    77.4 2298.78
    86.5 2294.19   109.6  2284.3   133.6 2271.87   182.1 2243.63   194.2 2231.58
  200.95    2227   202.2 2226.17   206.3 2225.49   215.8 2226.92   222.4 2227.84
   231.2 2230.53   250.5 2230.34   266.6 2232.09   274.6 2235.36   278.7 2235.94
   290.7 2236.71   330.8 2236.59   358.8 2239.79   366.8 2242.61   382.8  2250.8
   402.8 2267.28   406.8 2269.34   414.8 2270.05   422.8 2269.48   424.3 2270.02
#Mann= 4 ,-1,0
       0      .1       0  200.95    .045       0   215.8      .1       0
  352.52     .06       0
#XS Ineff= 2 , 0
                          237.18         2236.05
Permanent Ineff=
       F       F
Bank Sta=200.95,215.8
XS Rating Curve= 0 ,0
Exp/Cntr(USF)=0,0
Exp/Cntr=0.3,0.1

Type RM Length L Ch R = 1 ,6007    ,157.7,160.5,163.1
XS GIS Cut Line= 3
2229992.99657802440101.8193965512229878.90371156440330.005129473
2229865.17825394440474.122434477
#Sta/Elev= 30
       0 2308.61      15 2299.31    35.1 2288.96    47.8 2283.53    77.7 2272.32
   109.2 2258.35     129  2246.5   144.9 2237.95   152.2 2234.58   169.2  2224.7
   173.7 2223.21   198.6 2220.99   213.9  2219.8   217.8 2220.13   220.3 2221.05
   223.7 2222.53   236.3 2225.76   249.7 2224.52   273.4 2223.58   290.5 2224.03
   302.5 2225.69   322.6 2234.58   338.7 2246.83   346.7 2254.32   350.7 2257.42
   358.8 2258.65   374.8 2258.79   378.9 2261.58   392.6 2277.05   399.9 2283.11
#Mann= 4 ,-1,0
       0      .1       0   198.6    .045       0   220.3      .1       0
  295.12     .06       0
#XS Ineff= 2 , 0
                          241.35         2239.69
Permanent Ineff=
       F       F
Bank Sta=198.6,220.3
XS Rating Curve= 0 ,0
Exp/Cntr(USF)=0,0
Exp/Cntr=0.3,0.1

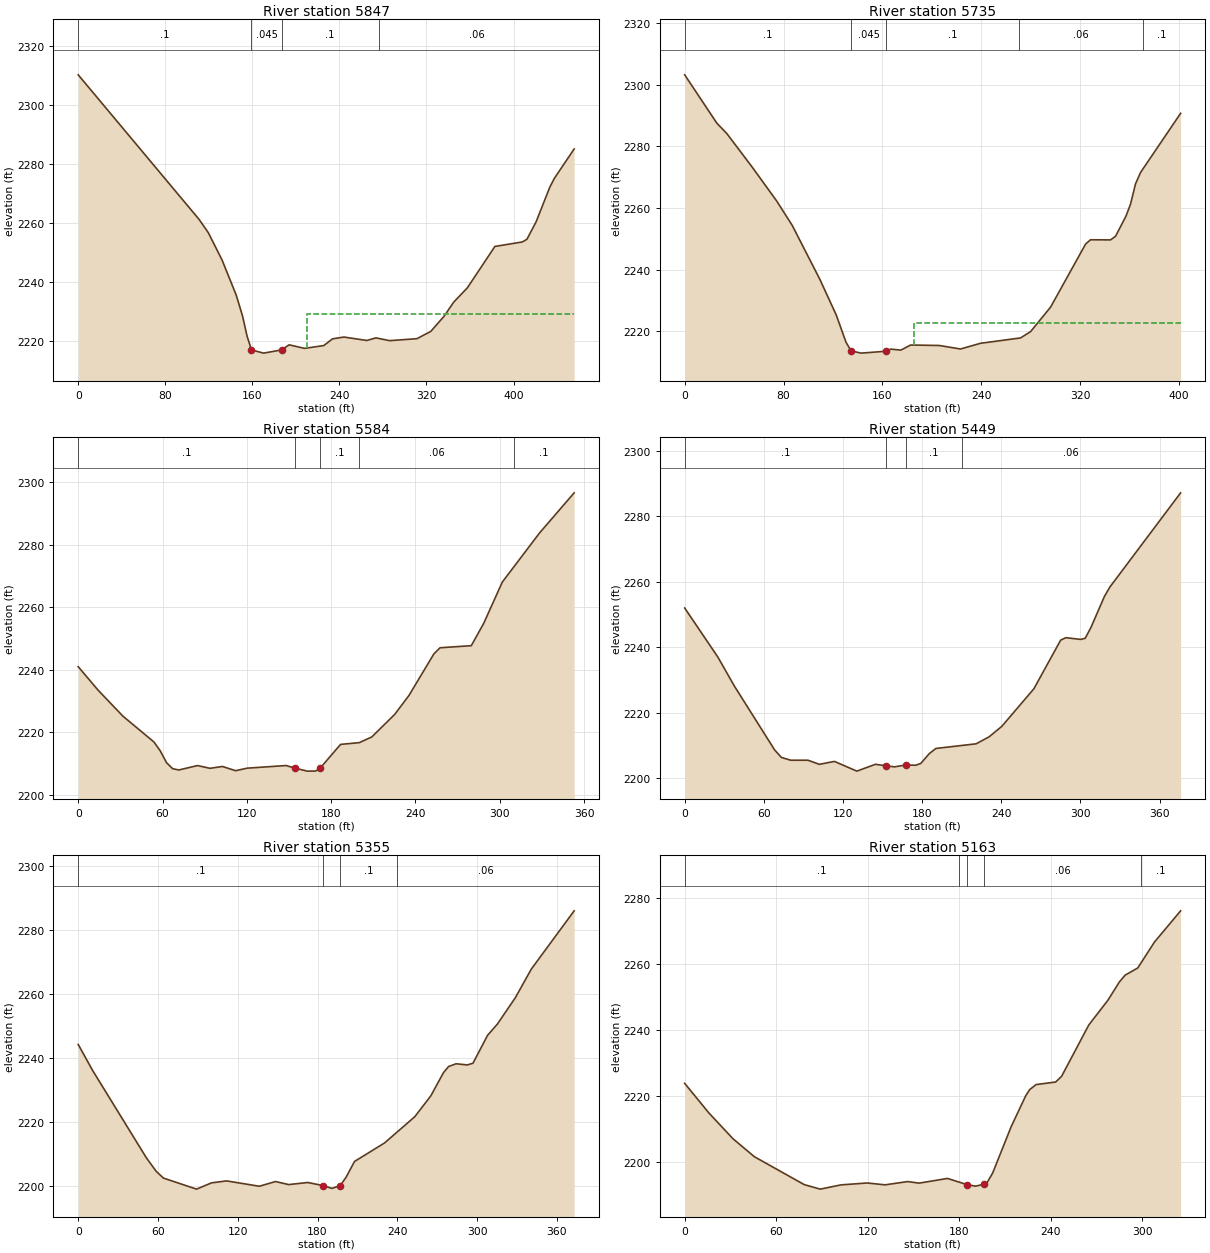
Type RM Length L Ch R = 1 ,5847    ,119.4,112.2,99.3
XS GIS Cut Line= 3
2229888.35163279440045.7630061862229745.08125383440233.591132383
2229812.23285254440442.507217272
#Sta/Elev= 30
       0 2310.33     111 2261.35   119.6 2256.78   132.2 2247.53   145.2 2235.65
     151 2228.57   155.2 2221.69  159.21 2217.07   170.3 2215.98   186.8 2217.06
   193.8 2218.79     208 2217.59   225.7 2218.55   233.7 2220.83   244.2 2221.43
   265.2 2220.27   273.6 2221.15   286.2 2220.21   311.3 2220.88     324 2223.36
   336.1 2228.45     345 2233.25   357.6 2238.13   382.9 2252.15   408.1 2253.67
   412.3 2254.58   420.7 2260.46   433.3 2272.21   437.5 2275.22   455.7  2285.2
#Mann= 4 ,-1,0
       0      .1       0  159.21    .045       0   186.8      .1       0
  276.23     .06       0
#XS Ineff= 2 , 0
                          210.13         2229.27
Permanent Ineff=
       F       F
Bank Sta=159.21,186.8
XS Rating Curve= 0 ,0
Exp/Cntr(USF)=0,0
Exp/Cntr=0.3,0.1

Type RM Length L Ch R = 1 ,5735    ,157.4,150.7,136.2
XS GIS Cut Line= 3
  2229696.183557440003.1676699122229676.45321167440203.044646494
2229706.47765021440401.205940874
#Sta/Elev= 30
       0 2303.21    26.1  2287.5    34.2 2284.12    54.3 2273.46    74.4 2262.32
      87  2254.4   109.3 2236.95   122.6 2225.37   130.6 2216.44   134.7 2213.68
   142.7 2212.95   162.8 2213.56   166.8 2214.25   174.9 2213.93   182.9 2215.58
     206 2215.43   223.2 2214.29   239.4 2216.14   271.8 2217.88   279.9 2219.93
   296.1 2227.88   324.4 2248.32   328.4 2249.72   344.6 2249.67   348.7 2250.89
   357.1 2257.39   360.8 2261.32   364.8 2267.84   368.9 2271.55   401.3 2290.73
#Mann= 5 ,-1,0
       0      .1       0   134.7    .045       0   162.8      .1       0
  270.85     .06       0  370.85      .1       0
#XS Ineff= 2 , 0
                          185.17         2222.65
Permanent Ineff=
       F       F
Bank Sta=134.7,162.8
XS Rating Curve= 0 ,0
Exp/Cntr(USF)=0,0
Exp/Cntr=0.3,0.1

Type RM Length L Ch R = 1 ,5584    ,137.3,135.5,132.4
XS GIS Cut Line= 2
2229503.77958381440092.4295134582229654.87068092440411.399607351
#Sta/Elev= 30
       0 2241.03    14.1 2233.55    31.8 2225.22    53.9 2216.95    58.4 2214.11
    62.8 2210.36    67.2 2208.41    71.6    2208    84.9 2209.41    93.8 2208.53
   102.6 2209.12     112 2207.77   120.3 2208.58     148 2209.42     154 2208.61
     163 2207.63     169 2207.66   172.1 2208.56   186.7 2216.18     200 2216.74
   208.9 2218.56   225.2 2225.77   235.4 2231.86   253.1 2245.13   257.5 2247.09
   279.7 2247.75   288.5 2254.85   301.8 2268.11   328.2 2283.76   352.9 2296.64
#Mann= 5 ,-1,0
       0      .1       0     154    .045       0   172.1      .1       0
     200     .06       0     310      .1       0
Bank Sta=154,172.1
XS Rating Curve= 0 ,0
Exp/Cntr(USF)=0,0
Exp/Cntr=0.3,0.1

Type RM Length L Ch R = 1 ,5449    ,94.7,93.7,91.6
XS GIS Cut Line= 3
2229350.47359321440127.554629588 2229486.8703283440300.838532032
2229575.22796173440428.656856113
#Sta/Elev= 30
       0 2252.02    25.2 2236.98    37.7 2228.13    68.2 2208.61    73.3 2206.33
    80.4 2205.47    93.5 2205.47   102.1 2204.22   113.5 2205.11   130.5 2202.14
   144.6 2204.23   152.82203.754     159 2203.45   167.92204.029   175.1 2203.94
     179  2204.5   185.3 2207.46   190.4 2209.07   220.9 2210.49   230.7 2212.62
   240.4 2215.84   264.7 2227.33     285  2242.2     289 2242.94   300.2 2242.41
   303.6 2242.76     308 2246.12   318.2 2255.59   322.3 2258.43   375.9 2287.23
#Mann= 4 ,-1,0
       0      .1       0   152.8    .045       0   167.9      .1       0
     210     .06       0
Bank Sta=152.8,167.9
XS Rating Curve= 0 ,0
Exp/Cntr(USF)=0,0
Exp/Cntr=0.3,0.1

Type RM Length L Ch R = 1 ,5355    ,192.1,192,190.2
XS GIS Cut Line= 2
2229268.65420117 440194.900153342229526.81479178440464.159410963
#Sta/Elev= 30
       0 2244.18    10.9 2236.01    51.3 2208.75    58.6 2204.58    64.1 2202.44
      89 2198.99   100.3 2200.95   111.6 2201.56   136.2 2199.89   148.4 2201.36
   158.3 2200.41   172.7 2201.06   184.3 2200.08   190.8 2199.22   197.1 2200.08
   201.6  2202.8   207.8 2207.63   230.4 2213.41   253.1 2221.59   265.2 2228.12
   274.7 2235.36   278.5 2237.27   284.2 2238.14   292.7 2237.78   296.9 2238.31
   307.9 2247.04   315.3 2250.56   328.8 2258.79   340.8 2267.72     373 2285.91
#Mann= 4 ,-1,0
       0      .1       0   184.3    .045       0   197.1      .1       0
     240     .06       0
Bank Sta=184.3,197.1
XS Rating Curve= 0 ,0
Exp/Cntr(USF)=0,0
Exp/Cntr=0.3,0.1

Type RM Length L Ch R = 1 ,5163    ,165.2,168.9,172.1
XS GIS Cut Line= 3
2229148.02309333440360.8874091172229316.15994916440501.573349716
2229377.06666735440588.215300938
#Sta/Elev= 30
       0 2223.95    15.8 2215.01    31.6 2207.19    45.7 2201.71    78.4 2193.25
    88.9 2191.89   102.5 2193.18   119.6 2193.75   131.4 2193.19   146.2 2194.18
   153.7 2193.71   172.3 2195.13   184.9 2193.28   190.6 2192.79   196.2 2193.37
   198.4 2193.97   201.9 2196.78     214 2210.79   223.6 2220.22   226.2 2222.07
   230.4 2223.58   243.2 2224.35   247.1 2226.09   264.9 2241.63   277.4 2249.11
     285  2254.7   288.8 2256.76     297 2258.91     308 2266.79   325.1 2276.23
#Mann= 5 ,-1,0
       0      .1       0     180     .06       0   184.9    .045       0
   196.2     .06       0  299.23      .1       0
Bank Sta=184.9,196.2
XS Rating Curve= 0 ,0
Exp/Cntr(USF)=0,0
Exp/Cntr=0.3,0.1

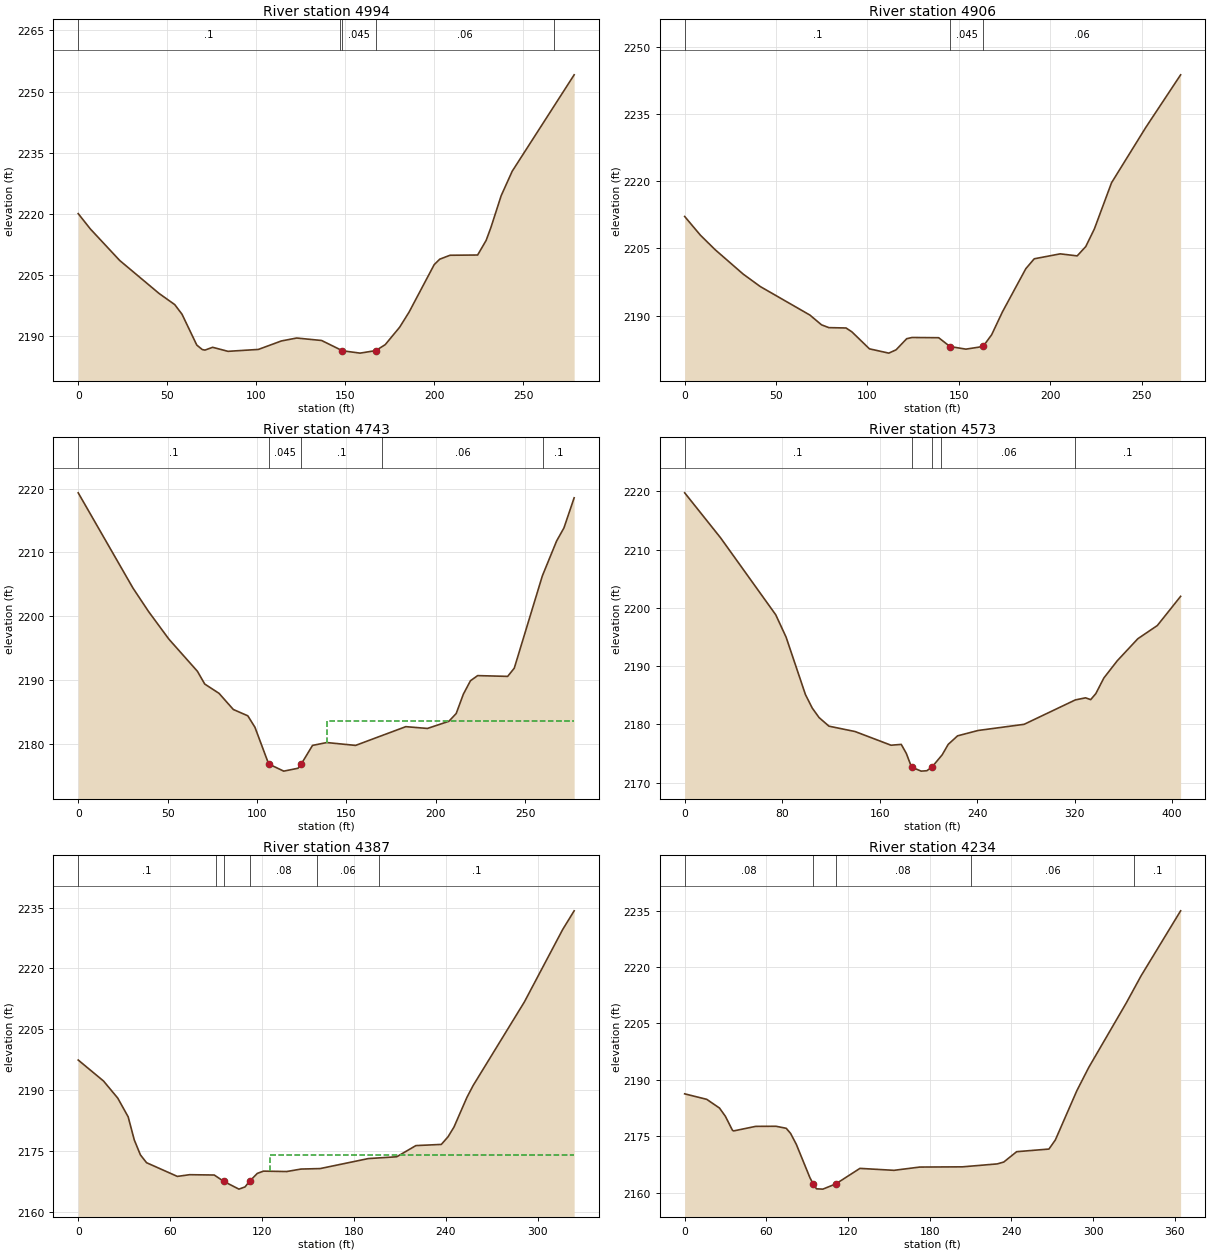
Type RM Length L Ch R = 1 ,4994    ,86.4,87.3,88
XS GIS Cut Line= 3
 2229088.2831417440430.8522180012229134.39432292440549.314948521
2229220.61376092  440673.7647324
#Sta/Elev= 30
       0 2220.01     6.8 2216.25    23.3  2208.5    45.4  2200.4    54.2 2197.66
    58.3 2195.29    66.6 2187.71    69.7 2186.61    71.2 2186.49    75.5 2187.17
    84.1 2186.18   101.2 2186.65   114.1 2188.73   122.7 2189.45   136.7 2188.84
   148.4 2186.32   158.3 2185.74   167.1 2186.36   172.4 2187.82   180.5  2192.1
   185.8 2195.82   199.9 2207.47     203 2208.81   208.8 2209.78   224.3 2209.84
   229.1 2213.45   231.8 2216.66   237.5 2224.39   243.7 2230.41   278.5  2254.1
#Mann= 5 ,-1,0
       0      .1       0  147.12     .06       0   148.4    .045       0
   167.1     .06       0  267.12      .1       0
Bank Sta=148.4,167.1
XS Rating Curve= 0 ,0
Exp/Cntr(USF)=0,0
Exp/Cntr=0.3,0.1

Type RM Length L Ch R = 1 ,4906    ,154.7,162.9,167.7
XS GIS Cut Line= 2
2229000.47442392440493.8527798052229142.01820562440725.469877132
#Sta/Elev= 30
       0 2212.12     8.6 2207.95    16.7  2204.7      32 2199.27    41.4 2196.48
    68.5 2190.13    74.9 2187.94    78.9 2187.32    88.3 2187.24    91.5 2186.38
   101.1 2182.59   111.7 2181.63   115.7 2182.37   121.5 2184.85   124.4 2185.12
     139 2185.07   145.2  2183.1   153.9 2182.52   163.3 2183.11     168 2185.74
   173.9 2190.84   186.7 2200.48   191.3 2202.68   205.5 2203.78   214.8 2203.33
   219.5 2205.42   224.2 2209.34   233.6 2219.65   252.4 2232.03   271.4 2243.73
#Mann= 3 ,-1,0
       0      .1       0   145.2    .045       0   163.3     .06       0
Bank Sta=145.2,163.3
XS Rating Curve= 0 ,0
Exp/Cntr(USF)=0,0
Exp/Cntr=0.3,0.1

Type RM Length L Ch R = 1 ,4743    ,170,170,170
XS GIS Cut Line= 2
2228923.47633056440502.7715802232228951.17636503440778.932529936
#Sta/Elev= 30
       0 2219.34    30.6 2204.43    39.4 2200.72    50.7 2196.42    66.7 2191.37
    70.8 2189.37    78.8 2187.91    86.8 2185.38    94.9 2184.39    98.9 2182.59
  106.57 2176.84     115 2175.72     123 2176.17   124.8 2176.83   131.1 2179.75
   139.1  2180.2   155.2 2179.75   183.3 2182.69   195.4 2182.41   207.4 2183.53
   211.5 2184.75   215.5 2187.78   219.5 2189.89   223.5 2190.69   240.3 2190.57
     244 2191.86   259.7 2206.32   267.7  2211.8   271.8 2213.85   277.5 2218.56
#Mann= 5 ,-1,0
       0      .1       0  106.57    .045       0   124.8      .1       0
     170     .06       0     260      .1       0
#XS Ineff= 2 , 0
                          138.93         2183.54
Permanent Ineff=
       F       F
Bank Sta=106.57,124.8
XS Rating Curve= 0 ,0
Exp/Cntr(USF)=0,0
Exp/Cntr=0.3,0.1

Type RM Length L Ch R = 1 ,4573    ,179.8,186.3,190.6
XS GIS Cut Line= 4
2228871.43384155440502.7715802232228758.48052313440616.907420803
2228814.35498265440791.5234546952228857.16412683440837.690178811
#Sta/Elev= 30
       0 2219.77    29.5 2212.03    74.7 2198.83    83.2 2194.99    99.1 2185.11
   104.7 2182.79   110.3 2181.16   118.4 2179.69   139.8 2178.77   169.3 2176.42
   177.7 2176.56   181.9 2174.99   186.1 2172.67     194 2171.97   198.7 2172.04
   202.9 2172.67   211.3 2174.78   216.2 2176.56   223.9 2178.03   240.7 2178.95
   278.5 2180.01   320.5  2184.2   328.9 2184.56   333.1 2184.25   337.3 2185.27
   343.9 2187.96   354.9 2190.92   371.8 2194.71   387.8 2196.98   406.9 2201.99
#Mann= 5 ,-1,0
       0      .1       0   186.1    .045       0   202.9      .1       0
  210.58     .06       0  320.58      .1       0
Bank Sta=186.1,202.9
XS Rating Curve= 0 ,0
Exp/Cntr(USF)=0,0
Exp/Cntr=0.3,0.1

Type RM Length L Ch R = 1 ,4387    ,160.4,152.6,142.5
XS GIS Cut Line= 3
2228599.86262965440572.7741611162228586.99501313440708.313055107
2228639.32332031440888.459686362
#Sta/Elev= 30
       0 2197.38    16.5 2192.21    25.8 2187.99    32.6 2183.37    36.6 2177.66
    40.6 2173.98    44.6 2172.05    64.7 2168.67    72.7 2169.09    88.8 2169.01
      952167.443   104.9 2165.53   108.9 2166.08   111.8 2167.45   116.9 2169.41
   120.9 2169.97   136.1 2169.87   145.4 2170.48   157.9  2170.6   189.4 2173.07
   207.9 2173.51   220.4 2176.27     237 2176.56   241.4 2178.45   245.3 2180.87
   253.7 2188.16   257.8 2191.11   291.2  2211.7   316.2 2229.57   323.7 2234.19
#Mann= 6 ,-1,0
       0      .1       0      90     .08       0      95    .045       0
   111.8     .08       0  156.15     .06       0  196.15      .1       0
#XS Ineff= 2 , 0
                          125.47         2173.85
Permanent Ineff=
       F       F
Bank Sta=95,111.8
XS Rating Curve= 0 ,0
Exp/Cntr(USF)=0,0
Exp/Cntr=0.3,0.1

Type RM Length L Ch R = 1 ,4234    ,195,195,195
XS GIS Cut Line= 2
2228392.13930573  440587.55047362228587.71833699440894.769037719
#Sta/Elev= 30
       0 2186.27    16.2 2184.81    25.6 2182.48    29.9 2180.29    35.1 2176.57
      36 2176.41    52.2 2177.62    67.1 2177.64    74.6  2177.1    77.8 2175.73
      82 2172.82      92 2163.94   94.39  2162.3    96.8    2161   101.5 2160.92
     111 2162.31   128.7 2166.44   153.7 2165.92   172.6 2166.79     204 2166.85
   229.5 2167.63   234.3 2168.12   243.8 2170.88   267.5 2171.58   272.2    2174
     288 2187.11   296.7 2193.27   324.4 2210.52   335.2 2217.69   364.2 2234.96
#Mann= 5 ,-1,0
       0     .08       0   94.39    .045       0     111     .08       0
     210     .06       0     330      .1       0
Bank Sta=94.39,111
XS Rating Curve= 0 ,0
Exp/Cntr(USF)=0,0
Exp/Cntr=0.3,0.1

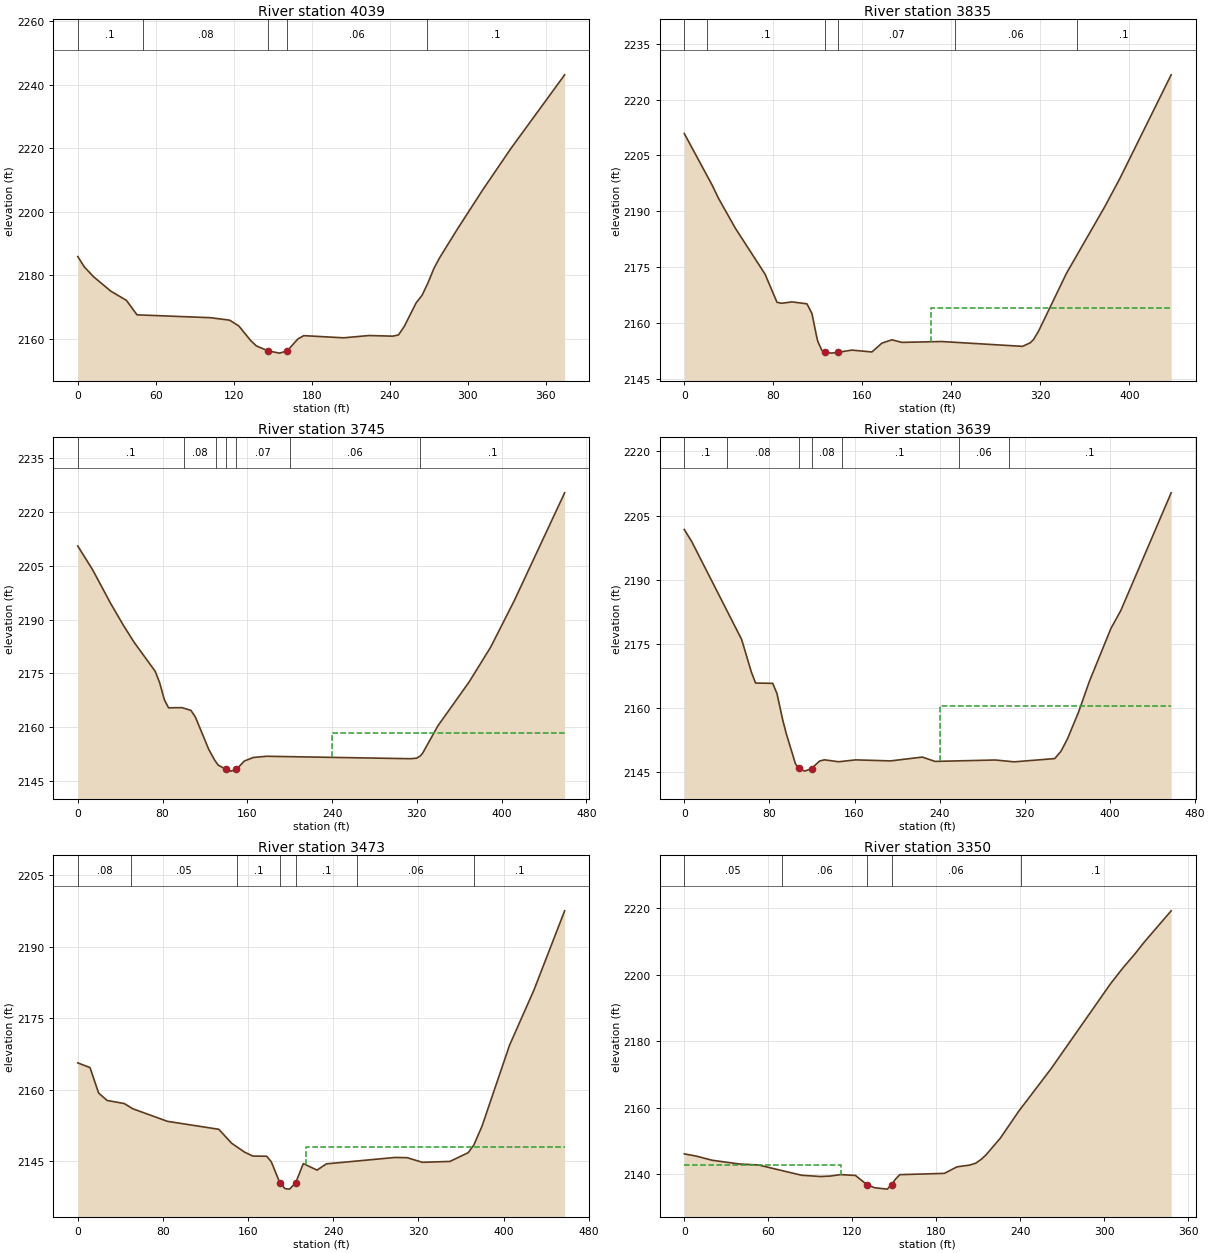
Type RM Length L Ch R = 1 ,4039    ,201.1,204.5,203.9
XS GIS Cut Line= 3
2228268.70103432 440620.018593982228254.40023089440727.486483459
2228381.17996217440961.652352439
#Sta/Elev= 30
       0 2185.94     5.2 2182.61    12.2 2179.58    25.4 2175.07    37.5 2172.14
    45.6  2167.6   102.1  2166.7   116.9 2165.92     124 2164.08   133.1  2159.5
   137.5 2157.81   146.4 2156.28   155.2 2155.55   161.1 2156.22   169.5 2160.04
     174 2161.05   204.6 2160.37   224.1 2161.09   242.3 2160.89   246.8 2161.27
   251.3 2163.97   260.4 2171.36     265 2173.77   269.5 2177.63   274.1 2182.21
   278.6 2185.64   292.3 2194.67   311.6 2206.89   333.2 2219.86   374.7 2243.13
#Mann= 5 ,-1,0
       0      .1       0      50     .08       0   146.4    .045       0
   161.1     .06       0  268.42      .1       0
Bank Sta=146.4,161.1
XS Rating Curve= 0 ,0
Exp/Cntr(USF)=0,0
Exp/Cntr=0.3,0.1

Type RM Length L Ch R = 1 ,3835    ,88.4,90,91.4
XS GIS Cut Line= 3
2228024.75803204440650.9731568032228130.55843452440858.761334652
 2228245.8904048441027.470084556
#Sta/Elev= 30
       0 2210.87    24.9 2197.08    30.9 2193.38    45.8 2185.46    72.6 2173.07
    83.3 2165.52    87.5 2165.24    96.7 2165.62   110.2 2165.11   114.7 2162.52
   119.2 2155.93   120.2 2154.84   123.7 2152.55   126.1 2152.13   132.1 2151.85
     138 2152.06   150.6 2152.66   168.6 2152.16   177.5 2154.52   186.5 2155.43
   195.5 2154.74   231.4 2154.97   303.9 2153.67   310.9 2154.63   313.8 2155.49
   318.5 2157.84   343.4 2173.29   377.8 2191.18   391.2 2198.66   437.5 2226.64
#Mann= 6 ,-1,0
       0     .08       0      20      .1       0   126.1    .045       0
     138     .07       0  243.17     .06       0  353.17      .1       0
#XS Ineff= 2 , 0
                          221.69         2163.97
Permanent Ineff=
       F       F
Bank Sta=126.1,138
XS Rating Curve= 0 ,0
Exp/Cntr(USF)=0,0
Exp/Cntr=0.3,0.1

Type RM Length L Ch R = 1 ,3745    ,107.5,105.7,104.3
XS GIS Cut Line= 3
2227962.32889699440675.7596737532228035.14725124440897.274331222
 2228198.5296091441053.925580703
#Sta/Elev= 30
       0 2210.56    14.1 2203.88      31 2194.54    43.2 2188.35    53.3 2183.62
    73.1 2175.56    77.3 2172.36    81.8 2167.58    85.7 2165.37    98.3 2165.42
   106.8 2164.66     111  2162.8   123.6 2153.78   129.3 2150.71   132.5 2149.38
  139.81  2148.2   144.7 2147.69  149.72  2148.2   157.3 2150.53   165.7  2151.5
   178.3 2151.84     314 2151.16   319.7  2151.3   323.3 2151.94   325.5 2152.71
   339.9 2160.34   369.6  2172.7   389.8 2182.37   412.1 2195.37   459.5  2225.4
#Mann= 7 ,-1,0
       0      .1       0     100     .08       0     130     .07       0
  139.81    .045       0  149.72     .07       0     200     .06       0
  323.18      .1       0
#XS Ineff= 2 , 0
                             240         2158.34
Permanent Ineff=
       F       F
Bank Sta=139.81,149.72
XS Rating Curve= 0 ,0
Exp/Cntr(USF)=0,0
Exp/Cntr=0.3,0.1

Type RM Length L Ch R = 1 ,3639    ,174.6,166.1,159.1
XS GIS Cut Line= 4
2227887.50345585440726.2725423532227893.22239652440813.962966033
2227972.33440919440972.1869913672228141.99631587441063.690042163
#Sta/Elev= 30
       0 2201.72     6.9 2198.96    53.9 2176.04      63 2168.45      67 2165.86
    83.1 2165.79    87.1  2163.4    92.5 2157.25    95.9 2153.98   104.4 2147.05
   107.4 2145.91   113.3 2145.28   119.62145.892   127.2 2147.65   131.7 2147.92
   145.1 2147.47     161 2147.91   193.8 2147.67   223.7 2148.56   235.6 2147.55
   292.1 2147.88     310 2147.45   348.1 2148.21     354 2149.94   359.9 2152.73
   370.5 2159.08   380.5 2166.14   400.9 2178.62   410.1 2182.75   457.5  2210.3
#Mann= 7 ,-1,0
       0      .1       0      40     .08       0   107.4    .045       0
   119.6     .08       0  147.88      .1       0  257.88     .06       0
  304.78      .1       0
#XS Ineff= 2 , 0
                          240.28         2160.61
Permanent Ineff=
       F       F
Bank Sta=107.4,119.6
XS Rating Curve= 0 ,0
Exp/Cntr(USF)=0,0
Exp/Cntr=0.3,0.1

Type RM Length L Ch R = 1 ,3473    ,120.6,122.9,123.9
XS GIS Cut Line= 3
 2227831.0242435440813.7893366062227810.22957252440974.908595019
2228084.36925911441083.830166924
#Sta/Elev= 30
       0 2165.64    11.5 2164.65    19.6 2159.31    27.6 2157.75    43.7  2157.1
    51.8    2156    84.2 2153.37   132.5  2151.7   144.6 2148.76   156.7 2146.91
   164.5 2146.08   177.5 2146.04   181.8 2144.89  189.86 2140.47   194.7 2139.24
     199 2139.14   204.7 2140.46   211.9  2144.5   224.8 2143.13   233.5 2144.44
   298.2 2145.79   309.4 2145.74   323.8 2144.77   349.6 2144.95   366.8 2146.79
   372.1  2148.4   379.8 2152.36   405.6 2169.32   428.6 2180.94   457.4 2197.55
#Mann= 7 ,-1,0
       0     .08       0      50     .05       0     150      .1       0
  189.86    .045       0   204.7      .1       0  262.46     .06       0
  372.46      .1       0
#XS Ineff= 2 , 0
                          214.26         2148.04
Permanent Ineff=
       F       F
Bank Sta=189.86,204.7
XS Rating Curve= 0 ,0
Exp/Cntr(USF)=0,0
Exp/Cntr=0.3,0.1

Type RM Length L Ch R = 1 ,3350    ,126.4,140.6,147.2
XS GIS Cut Line= 4
2227748.88425725441001.6947117222227792.63415341441091.768027349
2227880.99178684441138.9492879152228015.67283973   441198.998165
#Sta/Elev= 30
       0 2146.09     8.3 2145.45      20 2144.17    39.4 2143.05      53 2142.75
    83.9 2139.65    97.3 2139.28   104.2 2139.41   111.6 2139.85   122.3  2139.6
   130.4 2136.84   135.9  2135.9     145 2135.48   148.1 2136.87   151.1  2138.6
     154 2139.84   185.8 2140.22   194.8 2142.19   203.8 2142.71   208.2 2143.29
   212.5 2144.57   215.6 2145.82   225.7 2150.79   238.8 2158.87     262 2171.73
   304.5 2197.33   313.4 2202.12     322 2206.36   328.6 2209.88   347.8 2219.28
#Mann= 5 ,-1,0
       0     .05       0      70     .06       0   130.4    .045       0
   148.1     .06       0   240.3      .1       0
#XS Ineff= 2 , 0
           111.9 2142.77
Permanent Ineff=
       F       F
Bank Sta=130.4,148.1
XS Rating Curve= 0 ,0
Exp/Cntr(USF)=0,0
Exp/Cntr=0.3,0.1