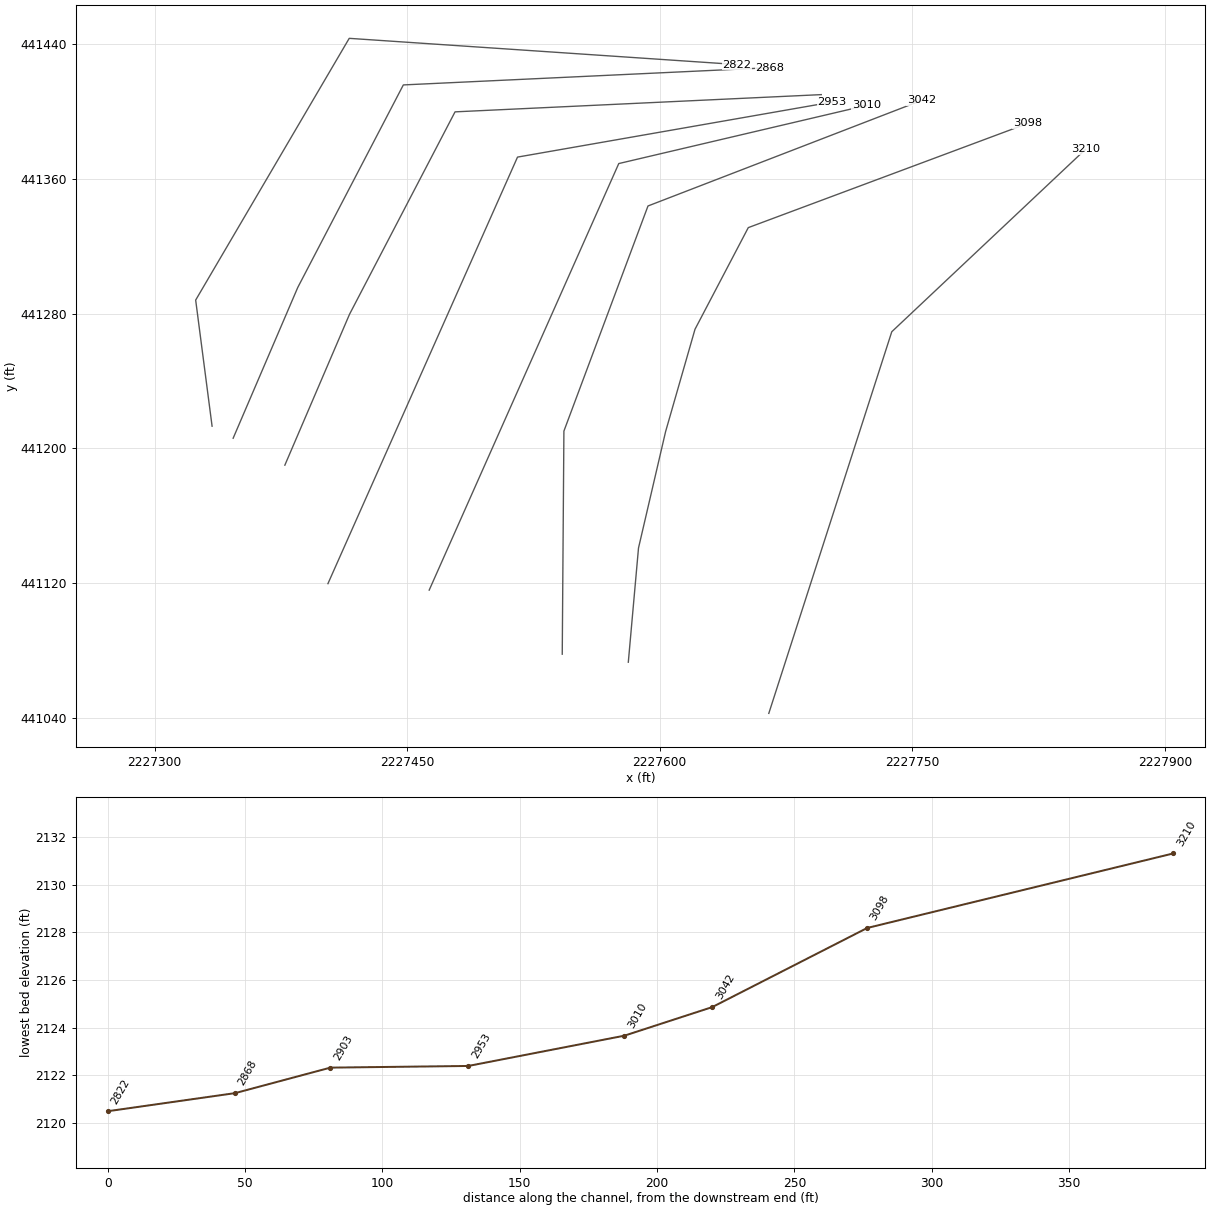
HEC-RAS study STLHSRN.prj: STLHSRN

--- STLHSRN.g01 (geometry) --- (continued)

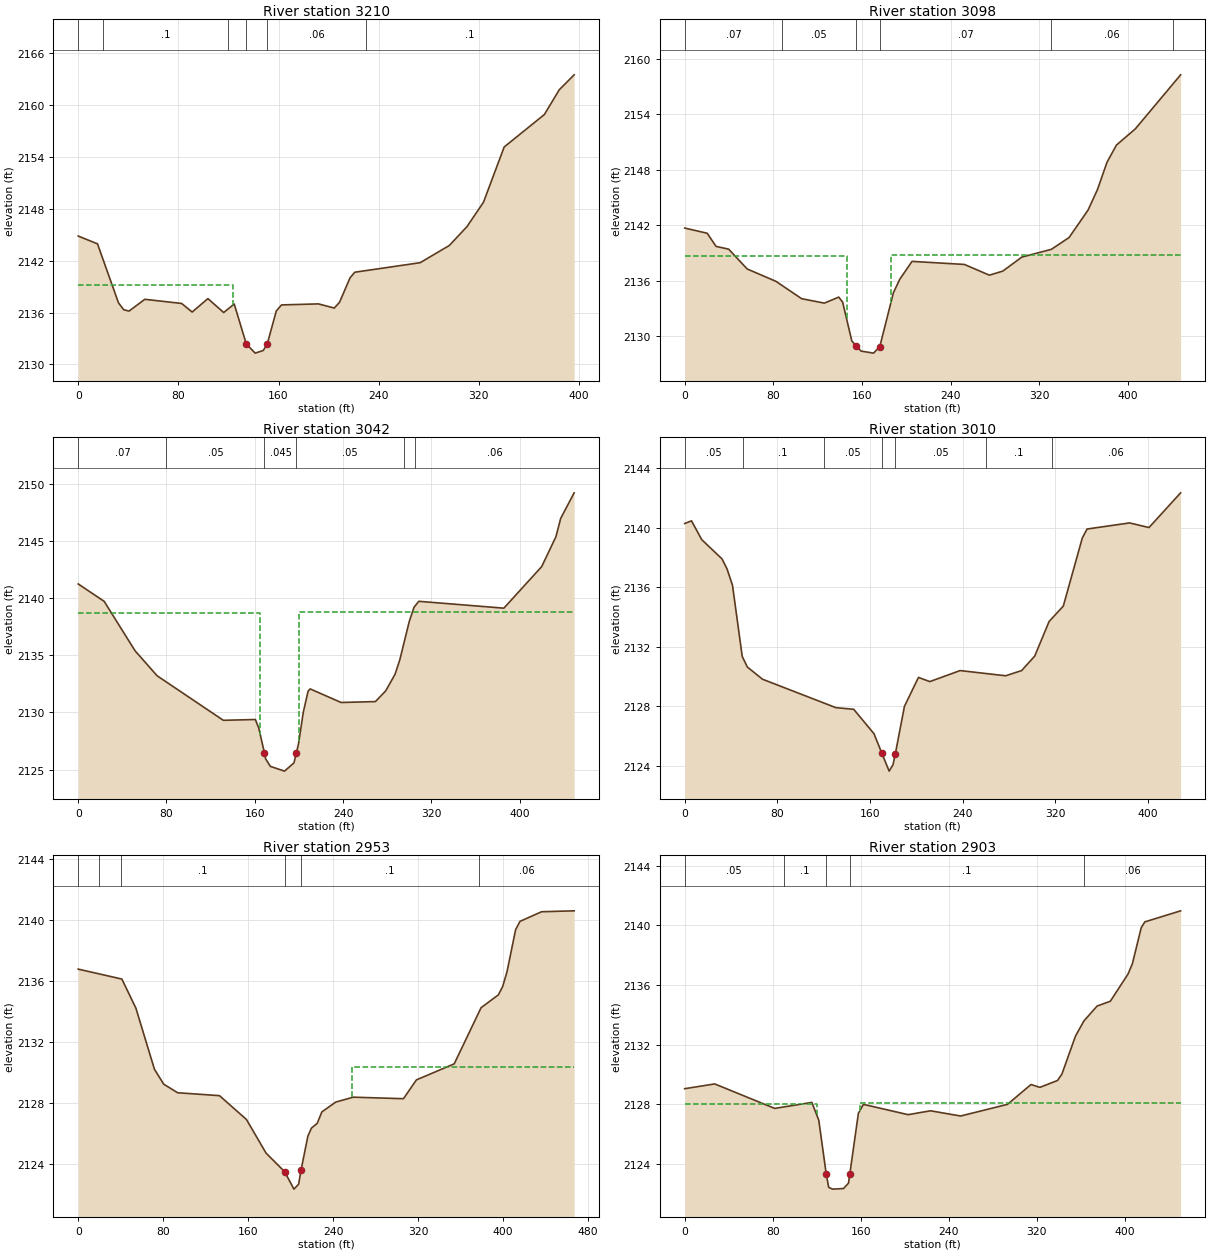
Type RM Length L Ch R = 1 ,3210    ,111.5,111.5,111.5
BEGIN DESCRIPTION:
structure xs 4
END DESCRIPTION:
XS GIS Cut Line= 3
2227664.80254963441042.5607566372227737.82991323441269.197402298
2227852.82702603441377.479355225
#Sta/Elev= 30
       0 2144.84    15.4 2143.94    32.2 2137.11    36.4 2136.32    40.6 2136.17
    53.2 2137.53    82.6 2137.05      91 2136.06   103.6 2137.61   116.2    2136
   124.6 2136.99   134.3 2132.35   141.4 2131.31   147.8 2131.62150.9469 2132.35
   158.2 2136.18   162.4 2136.88   191.9    2137   204.5 2136.52   208.7 2137.18
   217.1 2140.01   220.9 2140.66   273.1 2141.76   296.4 2143.75   310.5 2145.93
   323.7 2148.75   340.2 2155.13   372.3 2158.88   384.2 2161.74   396.1 2163.47
#Mann= 6 ,-1,0
       0     .05       0      20      .1       0     120     .07       0
   134.3    .045       0150.9469     .06       0     230      .1       0
#XS Ineff= 2 , 0
          123.77 2139.16
Permanent Ineff=
       F       F
Bank Sta=134.3,150.9469
XS Rating Curve= 0 ,0
Exp/Cntr(USF)=0,0
Exp/Cntr=0.5,0.3

Type RM Length L Ch R = 1 ,3098    ,56.4,56.4,56.4
BEGIN DESCRIPTION:
structure xs 3; 9.4 ft between structure and xs
END DESCRIPTION:
XS GIS Cut Line= 6
2227581.36977009441072.9544566182227587.42598339441140.773135851
2227603.52300859441209.9315800252227620.97709163441270.677035136
2227652.61961908441331.031801848 2227818.4572523 441392.88156128
#Sta/Elev= 30
       0 2141.69    20.3 2141.13    28.3 2139.71    39.7 2139.41    56.4 2137.27
    82.4 2135.93   105.5 2134.06     126 2133.58     139 2134.23   142.5 2133.69
   150.8 2129.49   154.6 2128.99   159.1  2128.4   170.4 2128.18176.02742128.891
   188.3  2134.7     194 2136.15   205.1 2138.09   252.3 2137.76   274.9  2136.6
     287 2137.04   304.1 2138.55   330.8 2139.39   346.8 2140.67   363.9 2143.63
   372.4 2145.85     381  2148.8   389.5 2150.65   406.6 2152.41   447.4 2158.24
#Mann= 6 ,-1,0
       0     .07       0   88.09     .05       0   154.6    .045       0
176.0274     .07       0  330.45     .06       0  440.45      .1       0
#XS Ineff= 2 , 0
             146  2138.7     186          2138.8
Permanent Ineff=
       F       F
Bank Sta=154.6,176.0274
XS Rating Curve= 0 ,0
Exp/Cntr(USF)=0,0
Exp/Cntr=0.5,0.3

Type RM Length L Ch R = 1 ,3042    ,32,32,32
BEGIN DESCRIPTION:
structure xs 2; 10.6 between structure and xs
END DESCRIPTION:
XS GIS Cut Line= 4
2227542.13835284441077.7097799212227543.12176241441210.199369875
2227593.05776789441343.8905164572227755.53782117441406.579670874
#Sta/Elev= 30
       0 2141.25    23.5 2139.73    51.5  2135.4    71.5 2133.21   131.5 2129.31
   160.5 2129.38   163.6 2128.63168.70892126.478   169.8 2125.94   174.1 2125.28
   186.9 2124.86   195.5 2125.58   197.8 2126.48   199.7 2127.29     204 2130.04
   208.3 2131.86   210.2 2132.06   238.2 2130.87   269.3 2130.95   278.6 2131.88
   287.1 2133.34   291.4  2134.6     300 2137.97   304.3 2139.21   308.6 2139.73
   385.7 2139.13     420 2142.77   432.9 2145.39   437.2 2146.99   449.4 2149.23
#Mann= 6 ,-1,0
       0     .07       0      80     .05       0168.7089    .045       0
   197.8     .05       0  295.21     .07       0  305.21     .06       0
#XS Ineff= 2 , 0
             165  2138.7     200          2138.8
Permanent Ineff=
       F       F
Bank Sta=168.7089,197.8
XS Rating Curve= 0 ,0
Exp/Cntr(USF)=0,0
Exp/Cntr=0.5,0.3

Type RM Length L Ch R = 1 ,3010    ,56.8,56.8,56.8
BEGIN DESCRIPTION:
structure xs 1
END DESCRIPTION:
XS GIS Cut Line= 3
2227463.12055022441115.7631482922227575.70515407441369.078506954
2227722.83276137441403.621510407
#Sta/Elev= 30
       0 2140.28     5.9 2140.46    14.7  2139.2    32.2 2137.91    36.6 2137.23
    41.3 2136.13    49.7 2131.36    54.1 2130.65    67.2 2129.83   130.6 2127.92
     146 2127.81   163.5 2126.17170.07282124.902   176.6 2123.66   179.9 2124.09
181.97282124.842   189.8 2128.01   201.9 2129.95   211.7 2129.67   237.9 2130.41
   277.2 2130.06     291 2130.41   302.3 2131.38   314.7  2133.7     327 2134.74
   343.4 2139.31   347.5 2139.91   384.2 2140.32     401 2140.01   428.3 2142.34
#Mann= 7 ,-1,0
       0     .05       0      50      .1       0     120     .05       0
170.0728    .045       0181.9728     .05       0     260      .1       0
  317.21     .06       0
Bank Sta=170.0728,181.9728
XS Rating Curve= 0 ,0
Exp/Cntr(USF)=0,0
Exp/Cntr=0.3,0.1

Type RM Length L Ch R = 1 ,2953    ,50.2,50.2,50.2
BEGIN DESCRIPTION:
structure xs 4
END DESCRIPTION:
XS GIS Cut Line= 3
 2227402.9901368441119.6012597872227515.57474065441372.916618448
2227702.47741503 441405.61574462
#Sta/Elev= 30
       0 2136.77    41.1 2136.12    54.3 2134.22    71.8 2130.22    80.5 2129.25
    93.6 2128.69     133  2128.5   158.4 2126.94   176.8 2124.75194.37142123.527
   203.1 2122.39   207.5 2122.71209.77132123.625   216.2 2125.85   219.6 2126.38
     225 2126.69   229.4 2127.44   242.5 2128.08     259  2128.4   306.2  2128.3
   318.4 2129.53     354 2130.58   379.3 2134.25   395.6 2135.09   399.6 2135.63
   403.7  2136.6   411.8 2139.35   415.9 2139.89   436.2 2140.52   466.9 2140.58
#Mann= 6 ,-1,0
       0      .1       0      20     .05       0      40      .1       0
194.3714    .045       0209.7713      .1       0  377.21     .06       0
#XS Ineff= 2 , 0
                          258.03         2130.34
Permanent Ineff=
       F       F
Bank Sta=194.3714,209.7713
XS Rating Curve= 0 ,0
Exp/Cntr(USF)=0,0
Exp/Cntr=0.5,0.3

Type RM Length L Ch R = 1 ,2903    ,34.7,34.7,34.7
BEGIN DESCRIPTION:
structure xs 3; 8.7 ft between structure and xs
END DESCRIPTION:
XS GIS Cut Line= 4
2227377.40272683441189.9666371932227415.78384178441279.522572073
 2227478.4729962441399.7833989122227695.96598091441410.018362899
#Sta/Elev= 30
       0 2129.05    27.3 2129.37    81.8 2127.73   115.6 2128.13   121.9 2126.94
 128.6532123.342   130.9 2122.44   134.5 2122.32   144.4 2122.36   148.9 2122.72
 150.1532123.362   157.9  2127.4   162.5    2128   203.1 2127.31   223.5 2127.57
   250.8 2127.22   293.4    2128   314.8 2129.33   322.9 2129.14   338.9  2129.6
   342.9 2130.03   355.2 2132.57   362.9 2133.59   374.9 2134.59   386.9 2134.91
   402.9 2136.72   406.9 2137.41     415 2139.84   418.3 2140.23   450.8 2140.97
#Mann= 5 ,-1,0
       0     .05       0      90      .1       0 128.653    .045       0
 150.153      .1       0  363.05     .06       0
#XS Ineff= 2 , 0
             120    2128     159          2128.1
Permanent Ineff=
       F       F
Bank Sta=128.653,150.153
XS Rating Curve= 0 ,0
Exp/Cntr(USF)=0,0
Exp/Cntr=0.5,0.3

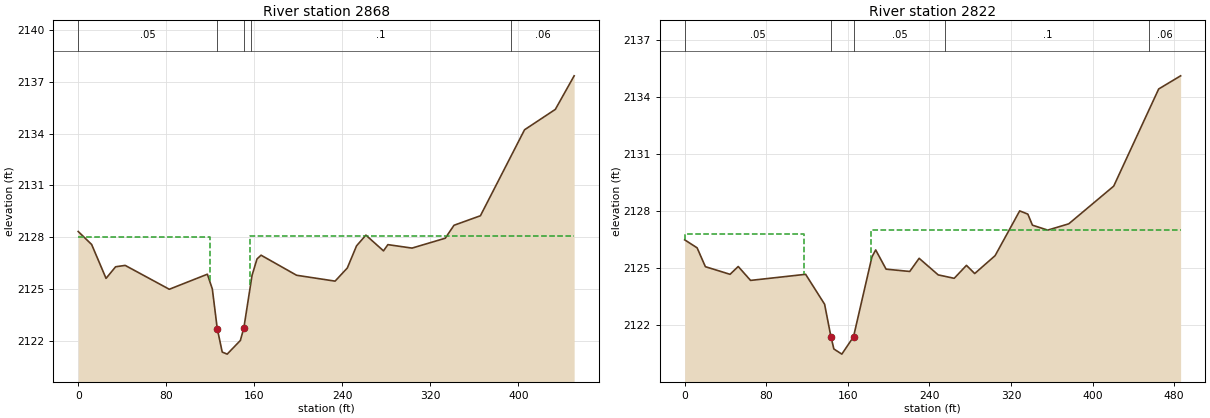
Type RM Length L Ch R = 1 ,2868    ,46.4,46.4,46.4
BEGIN DESCRIPTION:
structure xs 2; 18.4 ft between structure and xs
END DESCRIPTION:
XS GIS Cut Line= 4
2227346.69783488441205.9587684222227385.07894982441295.514703302
2227447.76810424441415.7755301412227665.26108895441426.010494127
#Sta/Elev= 30
       0 2128.34    12.2 2127.59    25.3 2125.63      34  2126.3    42.7 2126.38
    82.8    2125   117.4 2125.87   121.9 2125.02126.38452122.728   130.9 2121.37
   135.4 2121.25   147.4 2122.04150.58452122.775     158  2125.8   162.5 2126.75
   166.2 2126.97   198.5 2125.81   233.5 2125.47   244.6 2126.23     253 2127.51
   261.5 2128.13   277.5 2127.22   281.5 2127.58   303.4 2127.38   333.6 2127.95
   341.6  2128.7   365.6 2129.25   405.7 2134.22   433.7  2135.4   450.8 2137.34
#Mann= 5 ,-1,0
       0     .05       0126.3845    .045       0150.5845     .05       0
  157.43      .1       0  393.05     .06       0
#XS Ineff= 2 , 0
             120    2128   156.6          2128.1
Permanent Ineff=
       F       F
Bank Sta=126.3845,150.5845
XS Rating Curve= 0 ,0
Exp/Cntr(USF)=0,0
Exp/Cntr=0.5,0.3

Type RM Length L Ch R = 1 ,2822    ,,,
BEGIN DESCRIPTION:
structure xs 1
END DESCRIPTION:
XS GIS Cut Line= 4
2227334.18894459441213.0971341712227324.44051745441288.000530438
2227415.63404656 441443.444045982227645.69044957441427.899694426
#Sta/Elev= 30
       0 2126.49    12.2 2126.07    20.3 2125.08    44.5 2124.68    52.5 2125.09
    64.6 2124.36   118.6 2124.68   137.2 2123.11   143.4 2121.41   146.3 2120.76
   154.1 2120.49  165.55  2121.4   183.6 2125.59   187.3 2125.96   197.5 2124.95
   220.7 2124.83   229.9 2125.52   248.6 2124.65   264.3 2124.47   276.3 2125.15
   284.4 2124.72   304.4 2125.66   328.5 2128.01   336.5 2127.84     341 2127.26
     356    2127   376.6 2127.33   420.7 2129.31   464.8 2134.41   486.3  2135.1
#Mann= 5 ,-1,0
       0     .05       0   143.4    .045       0  165.55     .05       0
  255.54      .1       0  455.75     .06       0
#XS Ineff= 2 , 0
          117.11 2126.79  182.72         2126.99
Permanent Ineff=
       F       F
Bank Sta=143.4,165.55
XS Rating Curve= 0 ,0
Exp/Cntr(USF)=0,0
Exp/Cntr=0.3,0.1
LCMann Table=0

Chan Stop Cuts=-1
Use User Specified Reach Order=0
Composite Channel Slope=5